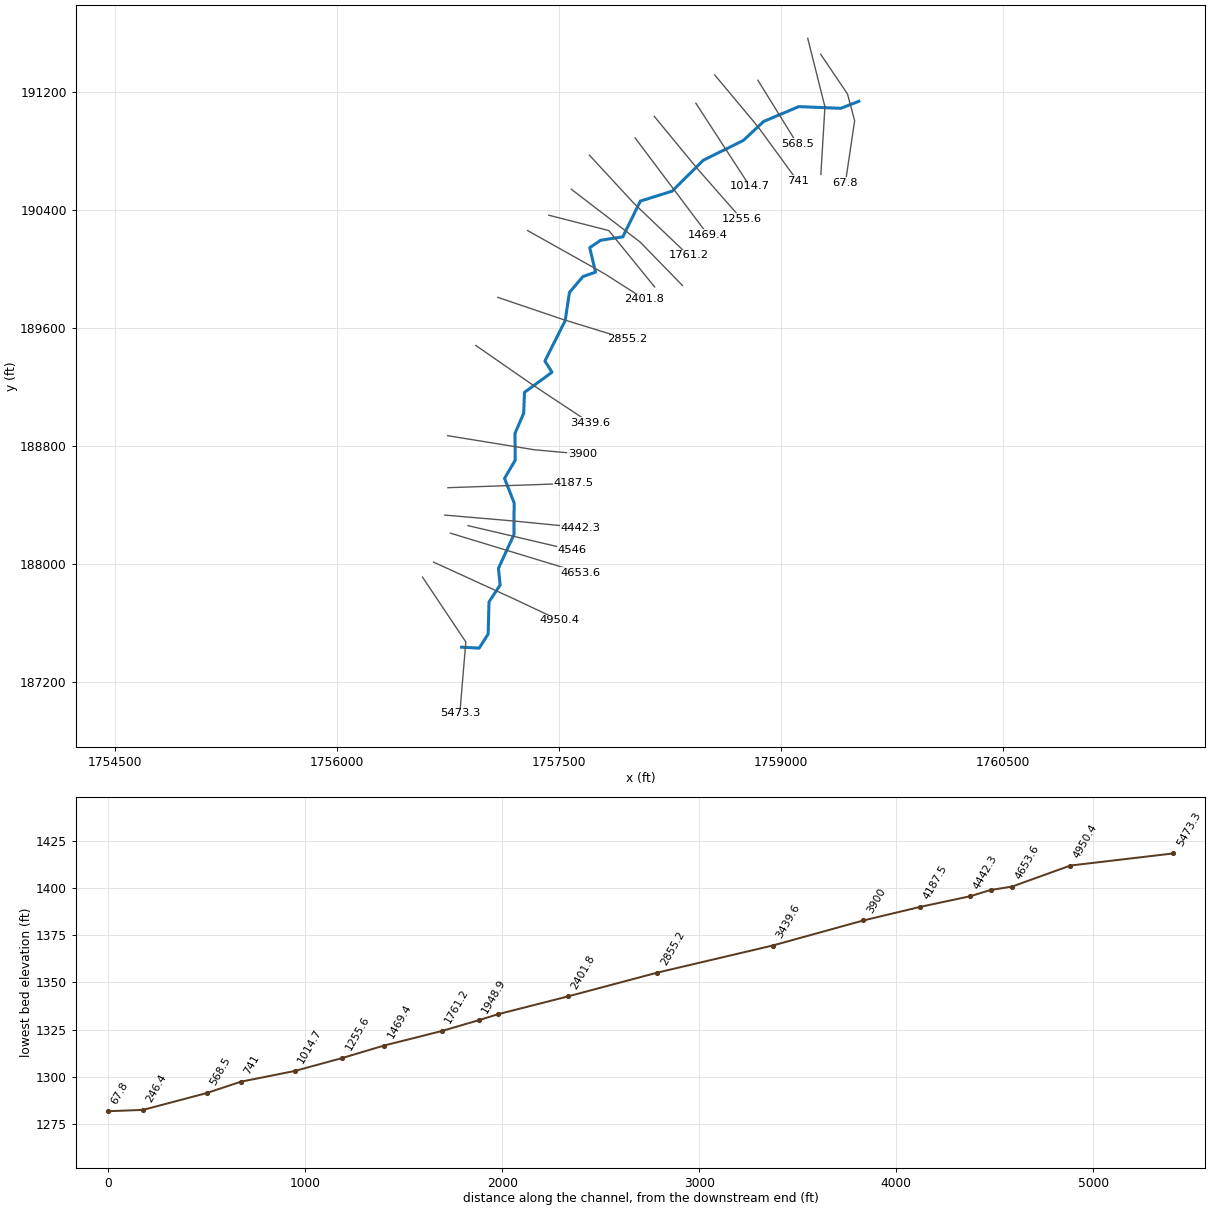
--- RthdFkPdFk.prj (project) ---

Proj Title=RthdFkPdFk
Current Plan=p01
Default Exp/Contr=0,0
English Units
Geom File=g01
Flow File=f01
Plan File=p01
BEGIN DESCRIPTION:
END DESCRIPTION:
DSS Export Rating Curves= 0
DSS Export Rating Curve Sorted= 0
DSS Export Volume Flow Curves= 0
DXF OffsetX= 0
DXF OffsetY= 0
DXF ScaleX= 0
DXF ScaleY= 0

--- RthdFkPdFk.p01 (plan) ---

Plan Title=Floodplain
Program Version=4.00
Geom File=g01
Flow File=f01
K Sum by GR=0
Std Step Tol=0.01
Critical Tol=0.01
Num of Std Step Trials=20
Max Error Tol=0.3
Flow Tol Ratio=0.001
Split Flow NTrial=30
Split Flow Tol=0.02
Split Flow Ratio=0.02
Log Output Level=0
Friction Slope Method=1
Unsteady Friction Slope Method=2
Unsteady Bridges Friction Slope Method=1
Global Log Level=0
CheckData=False
Run HTab=0
Run UNet=0
Run PostProcess=0
UNET Theta=0
UNET Theta Warmup=0
UNET ZTol=0
UNET ZSATol=0
UNET MxIter=0
UNET MaxInSteps=0
UNET DtIC=0
UNET DtMin=0
UNET MaxCRTS=0
UNET WFStab=0
UNET SFStab=0
UNET WFX=0
UNET SFX=0
UNET DSS MLevel=0
UNET DZMax Abort=0
UNET Convert EG Bridges=0
UNET Use Existing IB Tables=0
UNET Froude Limit=0
UNET Froude Power=0
Write IC File=0
Echo Input=False
Echo Output=False
Write Detailed=0

--- RthdFkPdFk.f01 (steady flow) ---

Flow Title=NFF Regression Equation
Program Version=4.00
Number of Profiles=1
Profile Names=P100yr
River Rch & RM=RthdFkPdFk,Main      ,5473.3
549.2222
River Rch & RM=RthdFkPdFk,Main      ,4950.4
557.4324
River Rch & RM=RthdFkPdFk,Main      ,4653.6
644.9756
River Rch & RM=RthdFkPdFk,Main      ,4187.5
656.7271
River Rch & RM=RthdFkPdFk,Main      ,2401.8
706.3457
River Rch & RM=RthdFkPdFk,Main      ,2045
752.4490
River Rch & RM=RthdFkPdFk,Main      ,246.4
779.4666
Boundary for River Rch & Prof#=RthdFkPdFk,Main      ,1
Up Type=0
Dn Type=3
Dn Slope=0.02259

--- RthdFkPdFk.g01 (geometry) ---

Geom Title=USGS 10m DEM
Program Version=4.00

River Reach=RthdFkPdFk      ,Main
Reach XY= 30
     1756841.838      187437.519     1756960.413      187430.771
     1757021.146      187526.209      1757026.93      187744.079
     1757102.124      187858.798     1757090.556      187971.588
     1757195.635      188200.062     1757196.598       188415.04
     1757132.009      188580.852     1757204.311      188704.247
     1757202.383      188885.483     1757261.188      189021.411
     1757266.787      189163.408     1757453.029      189300.014
     1757404.828      189375.208     1757541.719       189648.99
      1757570.64      189840.831     1757662.222      189947.838
     1757747.056      189977.723     1757707.531      190143.535
     1757781.761      190193.664     1757931.185      190216.801
      1758049.76      190458.771     1758264.737      190526.253
     1758474.895      190735.446     1758745.785      190869.445
     1758883.641      190998.625     1759120.791      191098.883
     1759404.214      191087.315     1759526.936      191135.012

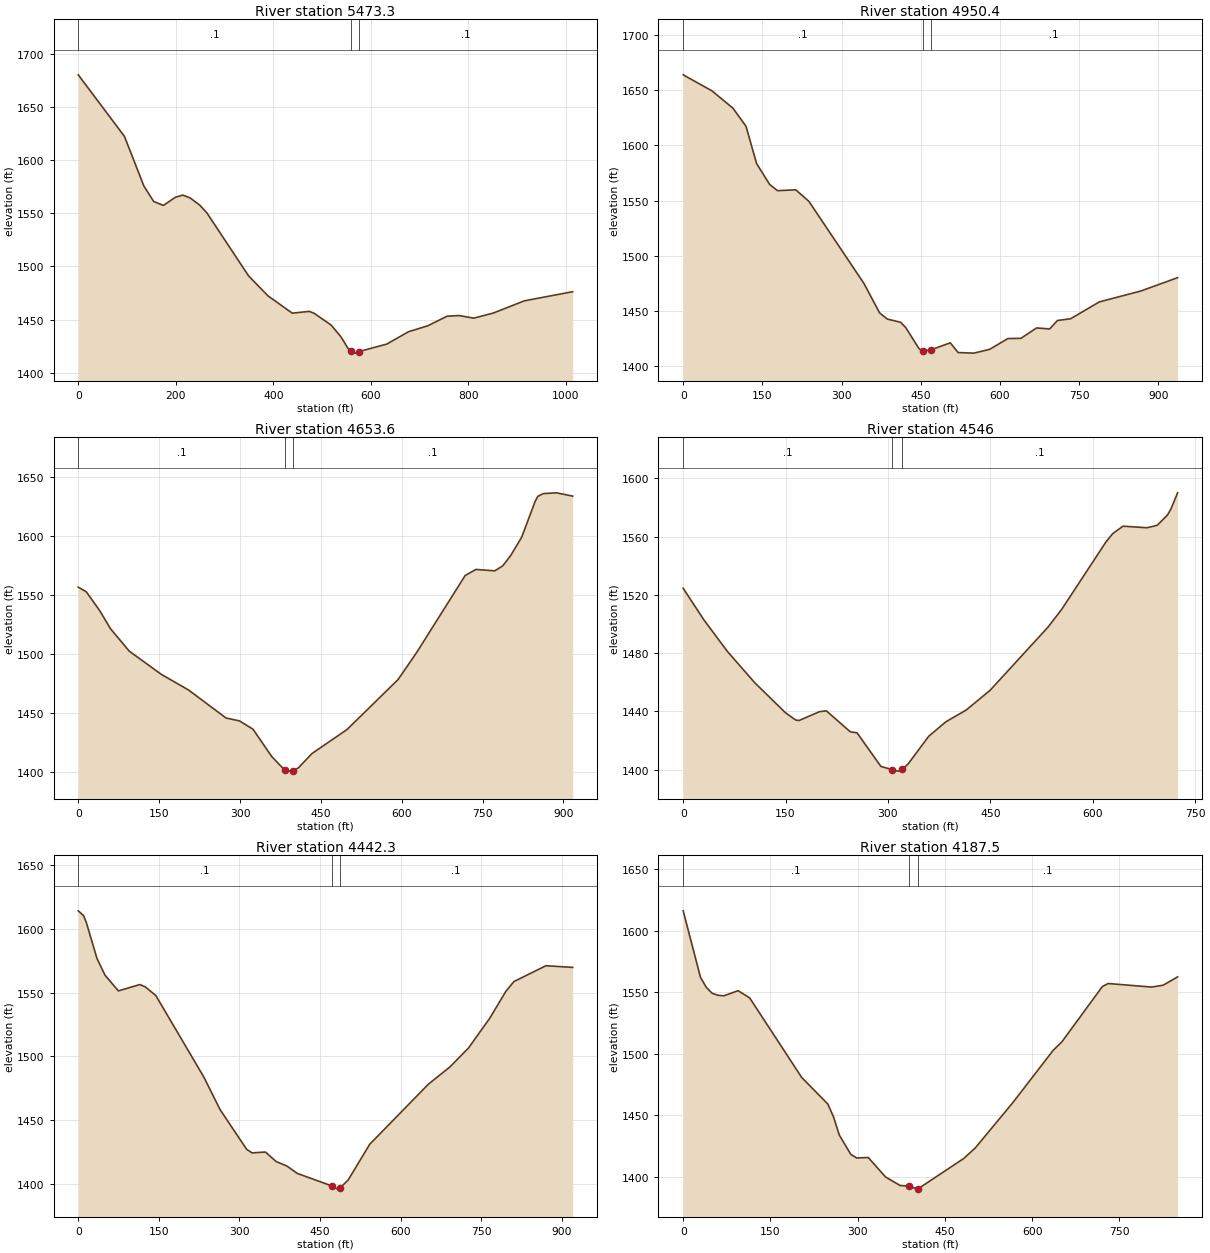
Type RM Length L Ch R = 1 ,5473.3  ,494,522.9,551.8
XS GIS Cut Line= 3
     1756577.138      187912.326     1756870.312      187472.609
       1756829.6      186989.088
#Sta/Elev= 30
       0 1680.38    94.7 1622.46   134.6 1575.66   154.6 1561.22   174.5 1557.47
   199.4 1565.21   214.4 1567.19   229.3 1564.57   249.3 1557.66   264.2 1550.14
     349  1491.3   388.9 1472.39   438.8 1456.07   473.6 1457.76   483.6 1455.97
   518.5 1444.86   538.4 1433.95   553.2 1422.81   559.7 1420.41   568.1 1418.47
   574.7 1419.83   632.5 1426.97     677  1438.6   716.6 1444.18   756.2 1453.23
     781 1453.83   810.7 1451.38   850.3 1456.07   914.7 1467.69  1013.7 1476.28
#Mann= 3 , 0 , 0
       0      .1       0   559.7    .045       0   574.7      .1       0
Bank Sta=559.7,574.7
XS Rating Curve= 0 ,0
Exp/Cntr=0.3,0.1

Type RM Length L Ch R = 1 ,4950.4  ,293.2,296.8,300.3
XS GIS Cut Line= 3
     1756652.056      188013.605     1757193.154      187765.716
     1757501.756      187619.984
#Sta/Elev= 30
       0 1663.96    54.6 1649.43    94.2 1633.78     119  1617.4   138.9 1583.75
   163.7 1564.75   178.6  1559.1   213.3 1559.84   238.1 1549.42   342.2 1475.25
     372 1448.48   386.9 1442.81   411.7 1439.97   421.6 1435.13   446.4 1416.25
   453.5 1413.95   468.5 1414.85   505.9 1421.36   520.8 1412.54   550.5 1412.02
   580.3 1415.41     615 1425.21   639.7  1425.4   669.4 1434.83   694.1  1433.9
   708.9 1441.56   733.7  1443.1   788.1 1458.36   867.2 1468.31   936.5 1480.32
#Mann= 3 , 0 , 0
       0      .1       0   453.5    .045       0   468.5      .1       0
#XS Ineff= 2 , 0
                          505.76         1420.58
Permanent Ineff=
       F       F
Bank Sta=453.5,468.5
XS Rating Curve= 0 ,0
Exp/Cntr=0.3,0.1

Type RM Length L Ch R = 1 ,4653.6  ,106.2,107.6,108.9
XS GIS Cut Line= 2
     1756766.237      188209.625     1757643.435      187942.005
#Sta/Elev= 30
       0 1556.51      15 1552.54    39.9 1536.56    59.8 1521.32    94.7 1502.32
   154.5 1482.57   204.4 1469.54   274.1 1445.78   299.1 1443.32     324 1436.37
   358.9 1413.16   383.5 1401.47   393.8 1400.83   398.5 1400.83   408.7  1403.8
   433.6 1415.74   498.4 1435.98   593.1 1478.27     628 1501.43   717.7 1566.37
   737.7 1571.49   772.6 1570.31   787.5 1574.58   802.5 1583.53   822.4 1598.67
   847.3 1628.89   852.3 1633.28   862.3 1635.65   887.2 1636.32   917.1 1633.51
#Mann= 3 , 0 , 0
       0      .1       0   383.5    .045       0   398.5      .1       0
Bank Sta=383.5,398.5
XS Rating Curve= 0 ,0
Exp/Cntr=0.3,0.1

Type RM Length L Ch R = 1 ,4546    ,100.7,103.7,106.7
XS GIS Cut Line= 2
     1756885.179        188260.6     1757590.336      188094.931
#Sta/Elev= 30
       0 1524.59      30 1503.12    64.9 1481.16   104.9 1459.71   149.9 1439.15
   164.8 1434.15   169.8 1433.83   199.8  1439.9   209.8 1440.44   244.8 1426.08
   254.8 1425.32   289.7  1402.3   306.3 1400.09   314.7 1399.07   321.3 1400.25
   329.7  1404.1   359.7 1422.97   384.7 1432.89   414.6 1440.99   449.6 1454.53
   534.5 1497.91   554.5 1510.07   619.4 1556.37   629.4 1562.13   644.4 1567.21
   679.4 1566.12   694.4 1567.78   709.4 1574.79   714.4 1578.78   724.4  1590.1
#Mann= 3 , 0 , 0
       0      .1       0   306.3    .045       0   321.3      .1       0
Bank Sta=306.3,321.3
XS Rating Curve= 0 ,0
Exp/Cntr=0.3,0.1

Type RM Length L Ch R = 1 ,4442.3  ,252.2,254.8,257.5
XS GIS Cut Line= 3
     1756728.457      188332.179     1757194.674       188291.99
     1757645.134      188247.623
#Sta/Elev= 30
       0 1614.24      10 1610.43    14.9 1605.25    34.8 1576.93    49.8 1563.72
    74.7 1551.37   114.5 1556.35   124.4 1554.67   144.4 1547.75     234 1483.59
   263.8 1458.36   313.6 1426.97   323.6  1424.2   348.5 1424.88   368.4 1417.43
   388.3 1413.93   408.2 1408.02   471.9 1398.31   482.9 1395.75   486.9 1396.42
   502.8 1403.06   542.6 1430.92     652 1478.17   691.8  1491.6   726.6 1506.54
   766.4 1530.06   796.2 1551.06   811.2 1558.73   870.8 1571.14   920.6 1569.82
#Mann= 3 , 0 , 0
       0      .1       0   471.9    .045       0   486.9      .1       0
Bank Sta=471.9,486.9
XS Rating Curve= 0 ,0
Exp/Cntr=0.3,0.1

Type RM Length L Ch R = 1 ,4187.5  ,291.6,287.5,283.4
XS GIS Cut Line= 2
     1756749.246        188517.6     1757598.832      188547.336
#Sta/Elev= 30
       0 1616.12    29.8 1562.01    39.8 1553.93    49.7 1549.19    59.7 1547.56
    69.6 1547.08    94.5 1551.25   114.3  1545.4   203.8 1480.75   248.6 1459.25
   258.5 1448.74   268.4 1433.99   288.3 1418.26   298.3  1415.4   318.2 1415.76
     348  1399.9   372.8 1393.08   388.1 1392.43   402.7 1390.07   403.1 1390.09
   482.2  1414.9   502.1 1423.48   566.7 1460.28   636.3  1502.9   651.2 1509.75
   720.8 1554.65   730.8 1557.08   805.4 1554.19   825.2 1555.71   850.1 1562.48
#Mann= 3 , 0 , 0
       0      .1       0   388.1    .045       0   403.1      .1       0
Bank Sta=388.1,403.1
XS Rating Curve= 0 ,0
Exp/Cntr=0.3,0.1

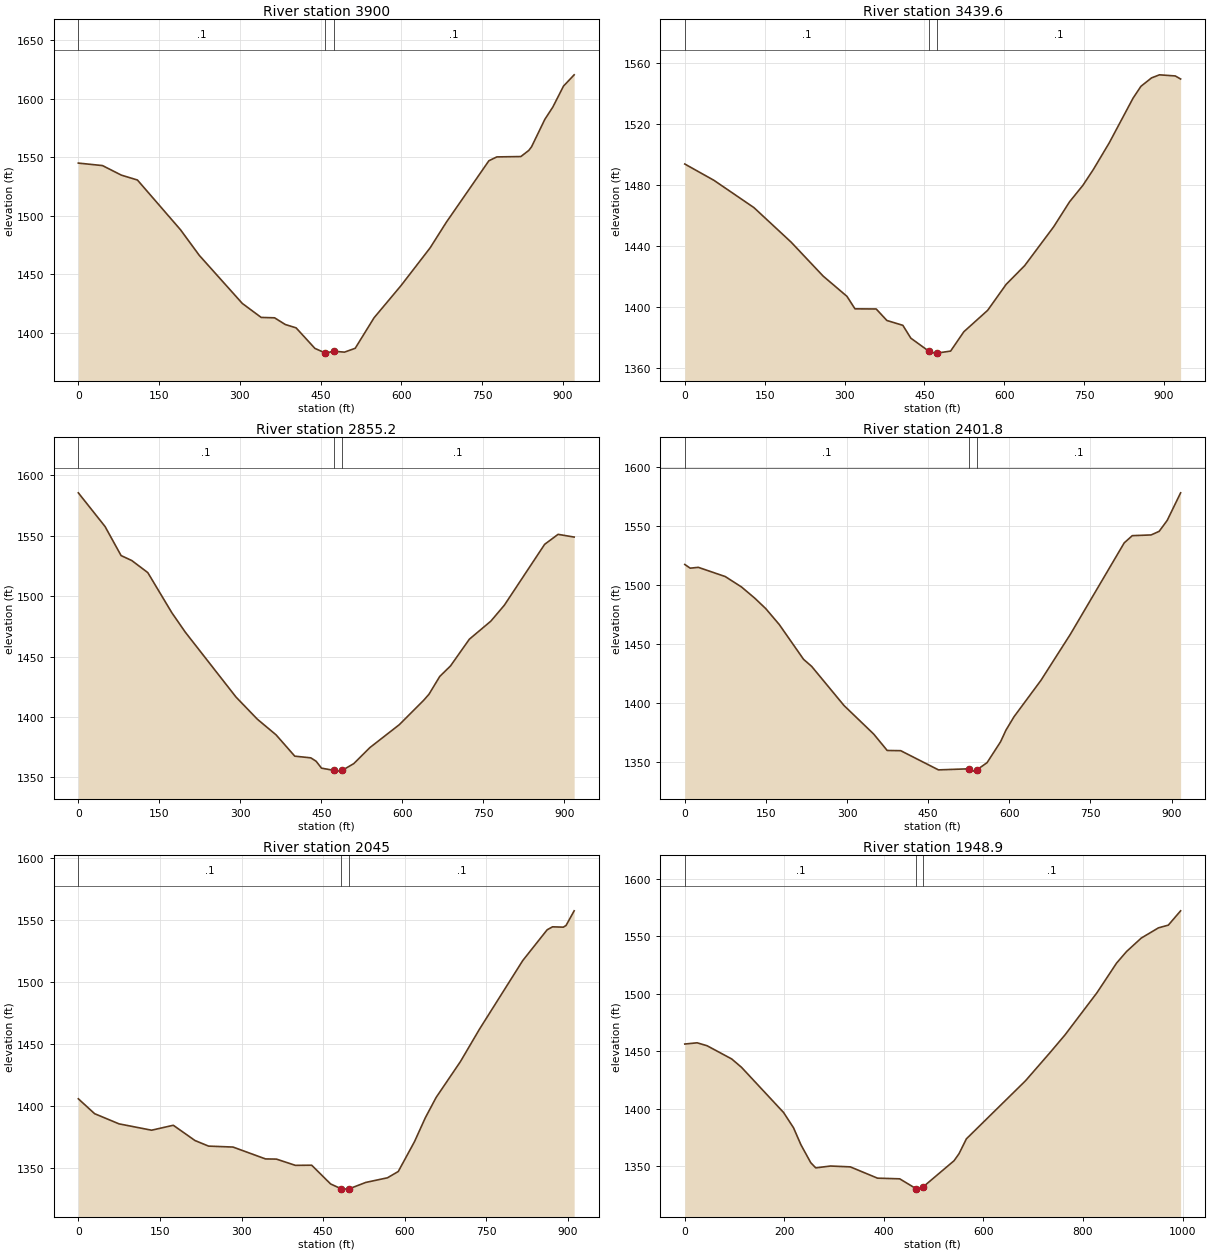
Type RM Length L Ch R = 1 ,3900    ,469.3,460.4,451.8
XS GIS Cut Line= 3
     1756746.848      188870.115     1757333.336        188774.6
     1757658.774      188745.144
#Sta/Elev= 30
       0 1544.97    44.9 1542.84    79.9  1534.7   109.8 1530.53   189.8  1488.1
   224.7 1466.26   304.6 1425.26   339.6 1413.34   364.5    1413   384.5 1407.27
   404.5 1404.44   439.4 1386.93   459.1  1382.9   459.4 1382.88   474.1  1384.5
   494.4 1383.72   514.3    1387   549.3 1413.02   599.2 1440.36   653.6 1472.76
   683.3 1494.33   762.6 1546.95   777.4 1550.24     822 1550.54   836.8  1555.8
   841.8 1558.81   866.5 1582.24   881.4 1592.77   901.2 1610.63     921 1620.25
#Mann= 3 , 0 , 0
       0      .1       0   459.1    .045       0   474.1      .1       0
Bank Sta=459.1,474.1
XS Rating Curve= 0 ,0
Exp/Cntr=0.3,0.1

Type RM Length L Ch R = 1 ,3439.6  ,574.1,584.4,591.9
XS GIS Cut Line= 3
     1756937.502       189481.21     1757331.227      189207.718
     1757707.826      188958.181
#Sta/Elev= 30
       0 1493.91    54.9 1483.15   129.8 1465.26   199.8 1442.51   259.7 1420.27
   304.6 1406.89   319.6  1398.7   359.5  1398.6   379.5 1391.05   409.5 1387.86
   424.5 1379.42   458.5 1370.81   469.4 1369.58   473.5  1369.6   499.2 1370.92
   524.1 1383.64   568.8 1397.72   603.5 1414.77   638.3  1427.1   692.9  1452.7
   722.6 1469.06   747.5 1479.81   767.3 1490.32   797.1  1507.8   841.8 1537.16
   856.7 1545.02   876.6 1550.52   891.4 1552.54   921.2  1551.8   931.2 1549.79
#Mann= 3 , 0 , 0
       0      .1       0   458.5    .045       0   473.5      .1       0
Bank Sta=458.5,473.5
XS Rating Curve= 0 ,0
Exp/Cntr=0.3,0.1

Type RM Length L Ch R = 1 ,2855.2  ,458.3,453.4,448.9
XS GIS Cut Line= 3
     1757086.954      189806.694     1757527.443      189656.931
     1757960.594      189523.654
#Sta/Elev= 30
       0 1585.39    49.5 1557.52    79.2  1533.5      99  1529.4   128.7  1519.4
   173.2 1486.24     198 1470.23     292 1416.52   331.6 1398.17   366.3 1385.21
   400.9  1367.6   430.6  1366.2   440.5 1363.38   450.4 1357.68   473.4 1355.85
   480.2 1355.22   488.4 1355.77   510.1  1361.4     540 1374.67   594.7  1393.7
   639.6 1413.78   649.5  1418.8   669.4  1433.5   689.4 1442.24   724.2 1464.28
   764.1 1479.28     789 1492.39   863.7 1542.77   888.6 1551.05   918.4  1548.8
#Mann= 3 , 0 , 0
       0      .1       0   473.4    .045       0   488.4      .1       0
Bank Sta=473.4,488.4
XS Rating Curve= 0 ,0
Exp/Cntr=0.3,0.1

Type RM Length L Ch R = 1 ,2401.8  ,362.2,356.8,350.2
XS GIS Cut Line= 3
      1757287.21      190259.657     1757809.104      189966.145
     1758076.885      189794.746
#Sta/Elev= 30
       0 1517.48      10 1514.36      25 1515.06    74.8 1507.26   104.8 1498.46
   129.7 1488.83   149.7 1480.12   174.6  1466.7   219.6  1437.2   234.5 1431.27
   294.4  1398.1   349.3 1373.95   374.2 1360.08   399.2  1359.9     469 1343.65
   524.9 1344.56   533.9  1342.6   539.9 1343.65   558.8 1349.74   583.8 1367.43
   593.8 1377.32   608.7 1388.64   658.4  1419.4     713 1458.52   812.4 1535.76
   827.3 1541.87   862.1 1542.48     877 1545.51   891.9 1554.79   916.7 1578.12
#Mann= 3 , 0 , 0
       0      .1       0   524.9    .045       0   539.9      .1       0
Bank Sta=524.9,539.9
XS Rating Curve= 0 ,0
Exp/Cntr=0.3,0.1

Type RM Length L Ch R = 1 ,2045    ,93.6,96.1,99.2
XS GIS Cut Line= 3
     1757431.038      190363.326     1757836.716      190259.252
     1758146.815      189876.938
#Sta/Elev= 30
       0  1405.9    29.9  1393.9    74.8 1385.69   134.6 1380.58   174.5 1384.56
   214.4 1372.25   239.3 1367.76   284.2    1367     344 1357.43     364 1357.29
   398.9 1352.25   428.8 1352.37   463.6 1337.25   482.7 1333.43   488.4 1333.09
   497.7 1333.36   528.2 1338.49     568 1342.22   587.9  1347.3   617.7 1371.34
   637.6 1390.59   657.5 1407.01   702.2 1435.94     737 1461.92   816.6 1517.29
   861.4 1542.08   871.3 1544.51   891.2 1544.24   896.2 1545.59   911.1  1557.4
#Mann= 3 , 0 , 0
       0      .1       0   482.7    .045       0   497.7      .1       0
Bank Sta=482.7,497.7
XS Rating Curve= 0 ,0
Exp/Cntr=0.3,0.1

Type RM Length L Ch R = 1 ,1948.9  ,191.4,187.7,184
XS GIS Cut Line= 3
     1757583.964      190538.553     1758048.404      190181.727
     1758334.432      189887.204
#Sta/Elev= 30
       0 1456.22    24.8 1457.29    44.7 1454.75    94.3 1443.22   114.2 1435.85
   198.5 1396.62   218.4 1383.39   233.3  1368.6   253.1 1352.96   263.1 1348.45
   292.8 1350.07   332.6 1349.32   387.2  1339.5   431.8 1338.92   464.5  1330.4
   466.6 1329.96   479.5 1332.14     541 1354.67   550.9 1360.74   565.8 1373.73
   684.6 1424.28   734.1 1448.92   763.8 1464.12   828.1 1500.86   867.6 1526.71
   887.4 1536.65   917.1 1548.43   951.7 1557.33   971.5 1559.69   996.2 1572.14
#Mann= 3 , 0 , 0
       0      .1       0   464.5    .045       0   479.5      .1       0
Bank Sta=464.5,479.5
XS Rating Curve= 0 ,0
Exp/Cntr=0.3,0.1

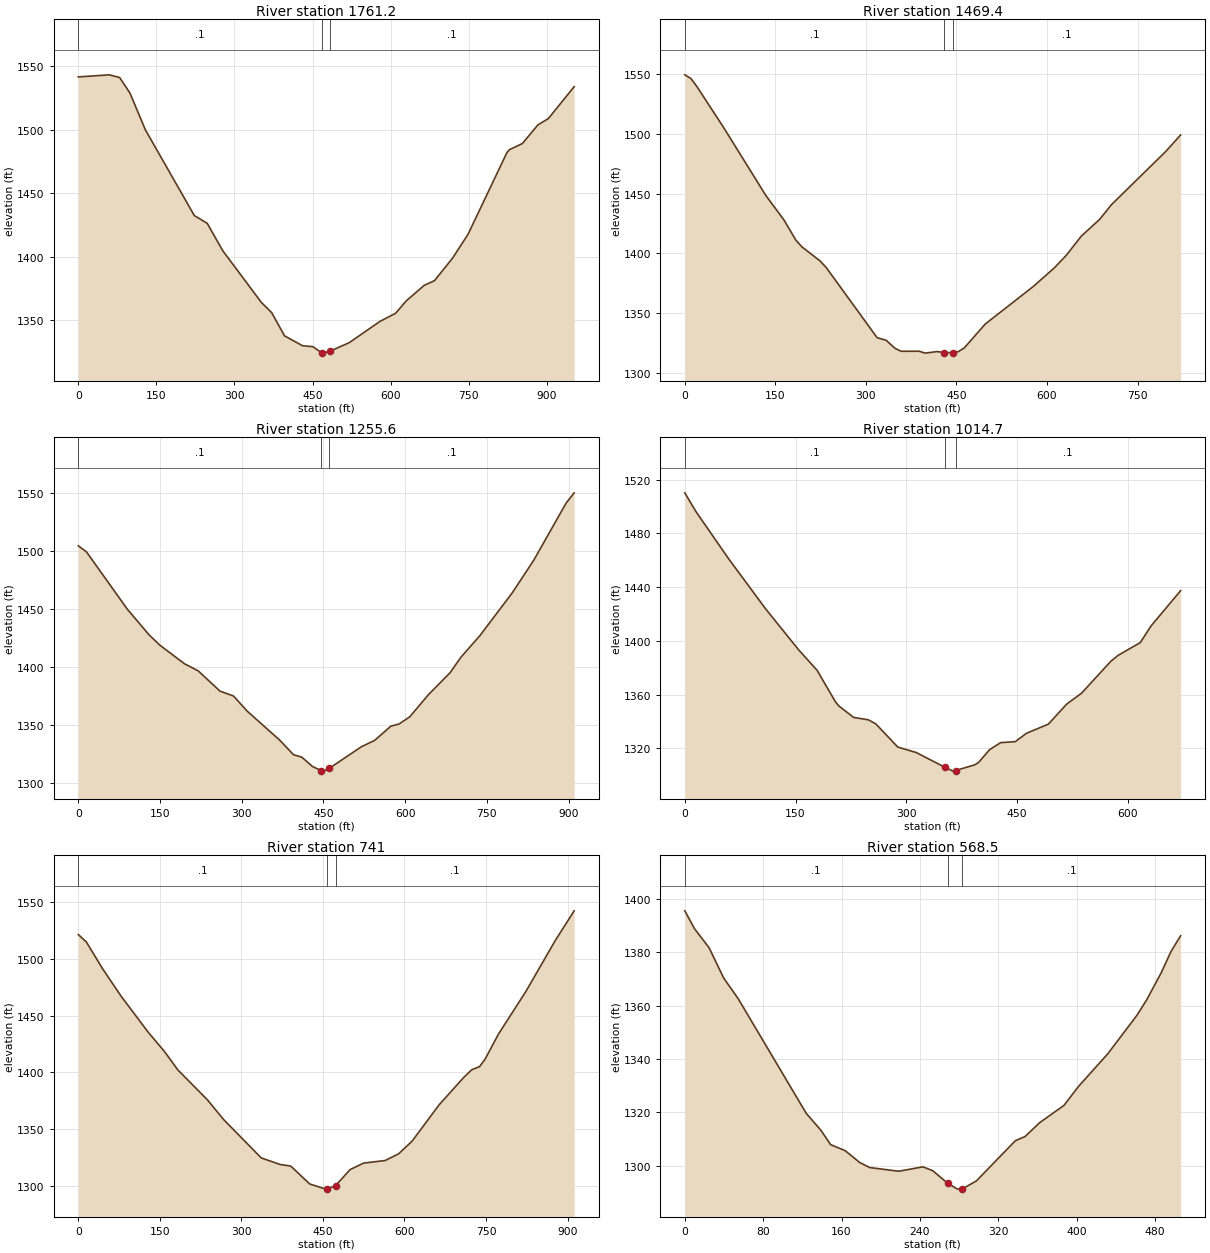
Type RM Length L Ch R = 1 ,1761.2  ,294.7,291.8,288.9
XS GIS Cut Line= 3
     1757705.244      190770.396     1758007.433      190442.597
     1758373.881      190092.329
#Sta/Elev= 30
       0  1541.5    59.4 1543.16    79.3 1541.05    99.1  1528.9   128.8 1499.93
   222.9 1432.45   247.7 1426.34   277.4 1404.86   351.7 1364.12   371.5 1356.13
   396.3  1337.8     431 1330.03   450.8  1329.3   468.1 1324.33   470.7 1324.22
   483.1 1325.65   520.4  1332.4     580 1349.28   609.8 1355.58   629.7 1365.14
   664.5  1377.5   684.4 1381.22   719.2 1398.98     749  1417.8   823.5 1481.89
   828.5 1484.28   853.4 1489.13   883.2  1503.8   903.1 1508.66   952.8 1533.85
#Mann= 3 , 0 , 0
       0      .1       0   468.1    .045       0   483.1      .1       0
Bank Sta=468.1,483.1
XS Rating Curve= 0 ,0
Exp/Cntr=0.3,0.1

Type RM Length L Ch R = 1 ,1469.4  ,212.9,213.8,215.5
XS GIS Cut Line= 2
     1758014.421      190886.884     1758507.181       190229.87
#Sta/Elev= 30
       0 1549.43      10 1546.42    19.9 1539.74    64.7 1505.03   134.4 1448.36
   164.2 1428.01   184.2 1410.97   194.1  1405.4     224 1393.73   233.9 1388.42
   318.6 1329.45   333.5  1327.3   348.4 1320.51   358.4 1318.09   388.2 1318.13
   398.2 1316.54   418.1 1317.85   429.5 1317.06   444.5 1316.93   452.9 1317.72
   462.9 1320.87   497.7 1340.89   577.4 1372.37   612.2 1387.91   632.1 1398.51
     657 1414.58   686.9 1428.33   706.8 1440.81   796.4 1485.15   821.3 1499.11
#Mann= 3 , 0 , 0
       0      .1       0   429.5    .045       0   444.5      .1       0
Bank Sta=429.5,444.5
XS Rating Curve= 0 ,0
Exp/Cntr=0.3,0.1

Type RM Length L Ch R = 1 ,1255.6  ,254.4,240.9,239.4
XS GIS Cut Line= 3
     1758144.429      191032.453     1758433.204      190680.901
     1758733.284      190338.506
#Sta/Elev= 30
       0 1504.27      15 1499.04      90 1449.56     130 1427.41     150 1418.42
     195 1402.49     220 1396.39     260 1378.92     285 1374.64     310 1361.63
     370 1336.48     395 1324.03     410 1321.99     430 1313.82   445.8 1310.36
     450 1309.87   460.8 1312.31   519.3  1330.8     544 1336.43   573.7 1348.65
   588.6  1350.5   608.4 1356.72     643 1375.98   682.6 1394.85   702.4 1408.21
     737 1426.69   796.4 1463.58     836 1491.84   895.4 1541.09   910.2    1550
#Mann= 3 , 0 , 0
       0      .1       0   445.8    .045       0   460.8      .1       0
Bank Sta=445.8,460.8
XS Rating Curve= 0 ,0
Exp/Cntr=0.3,0.1

Type RM Length L Ch R = 1 ,1014.7  ,272.4,273.7,273.2
XS GIS Cut Line= 2
     1758425.054      191121.936     1758790.376      190558.377
#Sta/Elev= 30
       0 1510.18    14.9 1496.38    59.7 1460.84   109.4 1423.88   154.2  1393.3
   179.1 1378.15     204 1354.65     209 1351.37   228.8 1342.97   248.7  1341.2
   258.7 1338.19   288.5 1320.93   313.4 1316.88     352 1305.97   363.2 1303.01
     367 1303.47     393 1307.75     398 1309.53   412.9 1319.02   427.8 1324.21
   447.7 1324.97   462.7 1331.17   492.5    1338   517.4 1352.98   537.3 1360.97
   577.1 1384.81     587 1389.23   616.9 1398.67   631.8 1411.29   671.6 1437.35
#Mann= 3 , 0 , 0
       0      .1       0     352    .045       0     367      .1       0
Bank Sta=352,367
XS Rating Curve= 0 ,0
Exp/Cntr=0.3,0.1

Type RM Length L Ch R = 1 ,741     ,176,172.5,169.9
XS GIS Cut Line= 3
     1758552.317      191313.648     1758843.869       190964.11
     1759112.775      190594.727
#Sta/Elev= 30
       0 1521.38    14.8 1514.84    44.5 1491.39    79.2 1466.79   128.6 1435.36
   158.3 1418.53   183.1 1402.22   237.5 1375.89   267.2  1358.6   336.4  1324.8
   371.1    1319   390.8  1317.6   425.5 1301.87   455.2  1297.3   458.1 1297.43
   473.1 1300.29   499.9 1314.48   524.7 1320.21   564.4 1322.47   589.3 1328.41
   614.1 1339.61   663.8 1371.56   708.4 1395.33   723.4 1402.31   738.2 1405.17
   748.2 1411.67     773 1433.87   822.7 1470.82   877.3 1516.06   912.1 1542.26
#Mann= 3 , 0 , 0
       0      .1       0   458.1    .045       0   473.1      .1       0
Bank Sta=458.1,473.1
XS Rating Curve= 0 ,0
Exp/Cntr=0.3,0.1

Type RM Length L Ch R = 1 ,568.5   ,328.6,322.2,308.2
XS GIS Cut Line= 2
     1758844.183      191277.693     1759110.387      190847.236
#Sta/Elev= 30
       0 1395.47     9.9  1388.8    24.8 1381.65    39.7 1370.31    54.6 1362.52
     124 1319.64   138.9 1313.35   148.9 1307.94   163.7  1305.7   178.6 1301.25
   188.6 1299.39   218.3 1297.99   243.1 1299.64   253.1  1298.2   268.2 1293.53
   277.9  1291.4   282.8  1291.3   283.2 1291.36   297.7  1294.4   337.4 1309.42
   347.3 1310.98   362.2 1316.17     387 1322.64   401.9 1329.75   431.7 1341.93
   461.5 1356.36   471.4 1362.11   486.3 1372.29   496.2 1380.19   506.1 1386.14
#Mann= 3 , 0 , 0
       0      .1       0   268.2    .045       0   283.2      .1       0
Bank Sta=268.2,283.2
XS Rating Curve= 0 ,0
Exp/Cntr=0.3,0.1

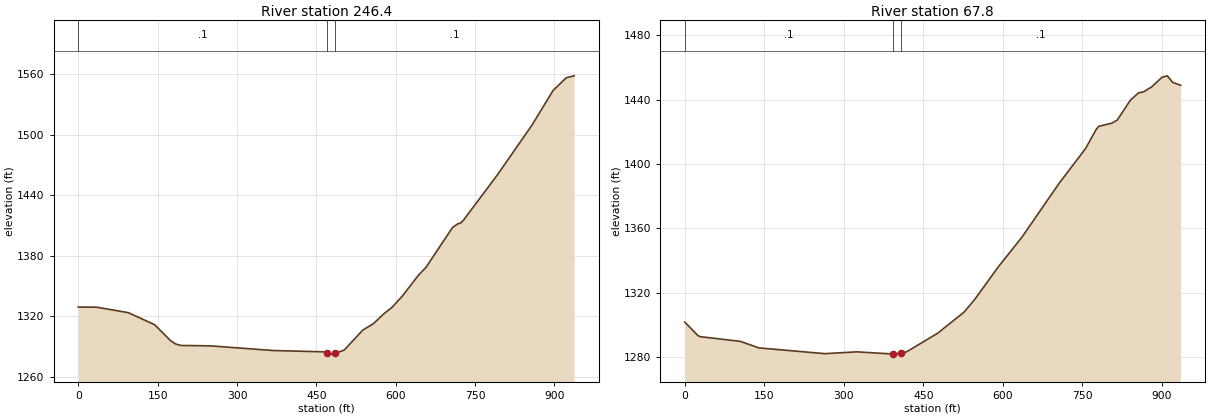
Type RM Length L Ch R = 1 ,246.4   ,178.8,178.6,185.9
XS GIS Cut Line= 3
     1759181.239      191561.351     1759297.517      191098.064
     1759270.138      190639.206
#Sta/Elev= 30
       0 1329.09    34.8 1328.95    94.5 1323.54   144.3 1311.57   174.2 1295.84
   184.1 1292.41     194 1290.98   248.8 1290.62   368.2 1285.97   462.7  1284.7
   470.2 1283.73   477.7 1282.39   485.2 1283.18   502.6 1286.38   537.6 1306.19
   557.6 1312.53   577.6 1322.45   592.6 1328.62   612.6 1340.01   642.5 1360.42
   657.5 1368.69   707.5 1408.11   717.5 1411.79   722.5 1412.38   727.5  1414.9
   792.4 1460.42   857.4 1509.46   897.4 1543.95   922.3 1556.63   937.3 1558.54
#Mann= 3 , 0 , 0
       0      .1       0   470.2    .045       0   485.2      .1       0
Bank Sta=470.2,485.2
XS Rating Curve= 0 ,0
Exp/Cntr=0.3,0.1

Type RM Length L Ch R = 1 ,67.8    ,48.2,67.8,87.1
XS GIS Cut Line= 4
     1759268.977      191453.274     1759450.222      191184.239
     1759498.365      191002.994     1759436.062      190583.865
#Sta/Elev= 30
       0  1301.6      25 1293.13    29.9  1292.5   104.8 1289.61   139.7 1285.55
   264.5 1281.96   324.4 1283.09   392.3 1281.74   393.5 1281.67   407.3  1282.3
   418.2 1283.04   477.4 1294.73   526.9 1307.78   546.8 1315.56   591.7    1336
   636.6  1354.6   706.3 1387.92   756.2 1409.52   776.1 1421.36   781.1 1423.41
     806  1425.4     816 1427.29   840.9 1439.68   855.9 1444.16   865.9 1444.91
   880.8  1447.9   900.8 1453.98   910.7 1454.84   920.7 1450.78   935.7 1448.98
#Mann= 3 , 0 , 0
       0      .1       0   392.3    .045       0   407.3      .1       0
Bank Sta=392.3,407.3
XS Rating Curve= 0 ,0
Exp/Cntr=0.3,0.1

Chan Stop Cuts=-1
Use User Specified Reach Order=0